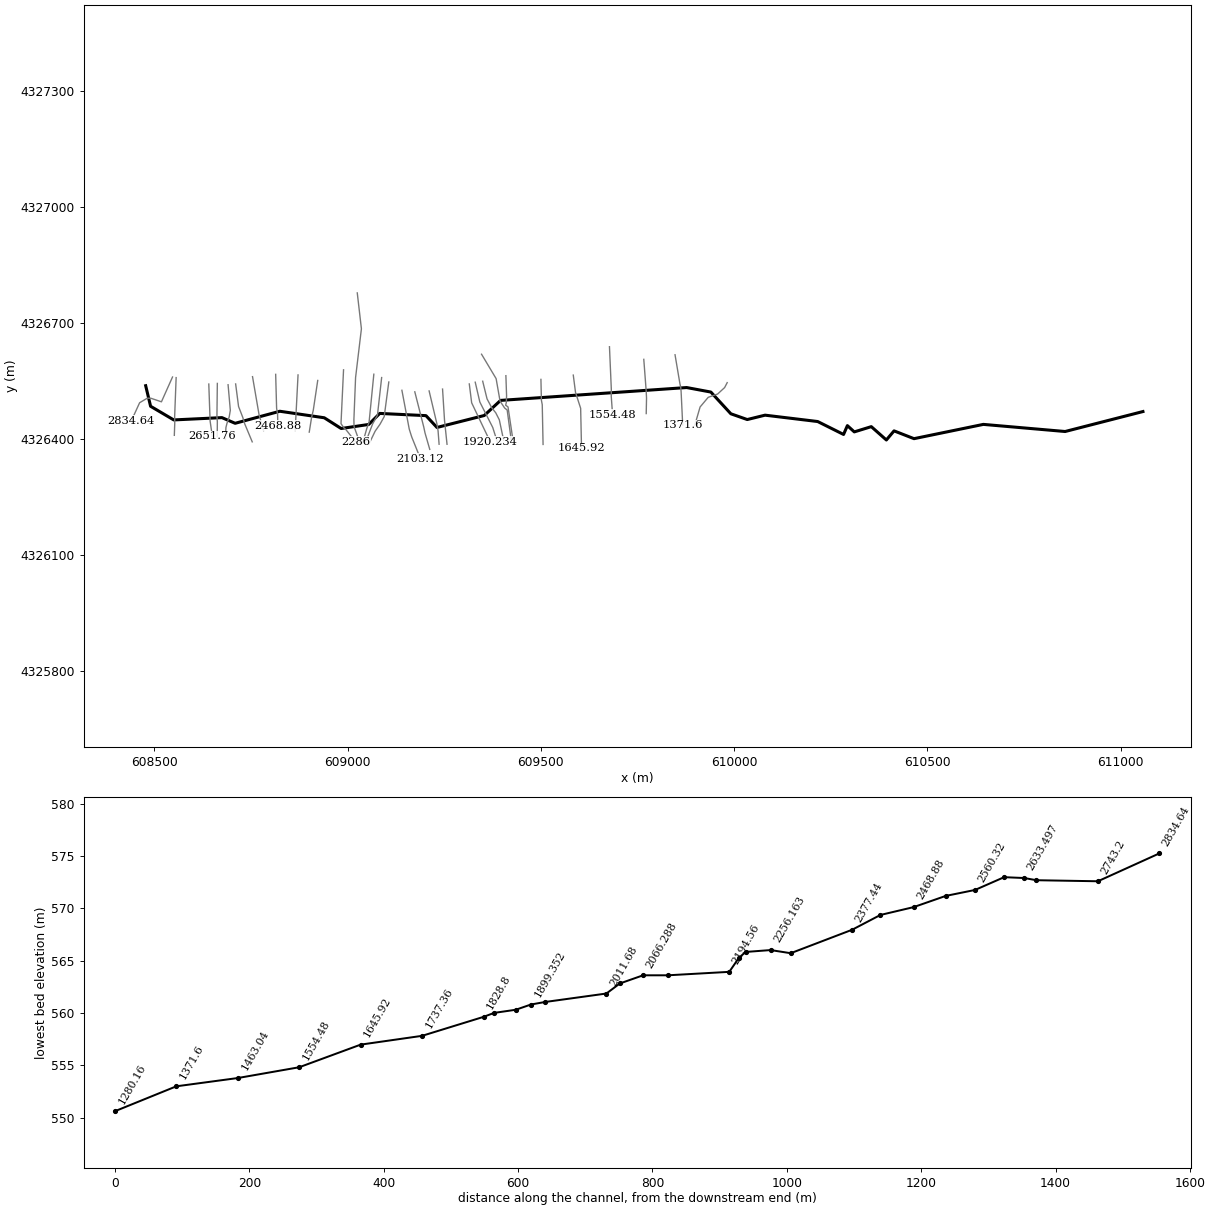
--- SBHaddixRun.prj (project) ---

Proj Title=SBHaddixRun
Current Plan=p01
Default Exp/Contr=0.3,0.1
SI Units
Geom File=g01
Flow File=f01
Plan File=p01
Y Axis Title=Elevation
X Axis Title(PF)=Main Channel Distance
X Axis Title(XS)=Station
BEGIN DESCRIPTION:
September 2018
Tucker County ABFE Study
US Army Corps of Engineers, Pittsburgh District
NAD 1983 UTM 17N (meters)
END DESCRIPTION:
DSS Export Rating Curves= 0
DSS Export Rating Curve Sorted= 0
DSS Export Volume Flow Curves= 0
DXF OffsetX= 0
DXF OffsetY= 0
DXF ScaleX= 1
DXF ScaleY= 10

--- SBHaddixRun.p01 (plan) ---

Plan Title=SBHaddixRun_plan
Program Version=5.05
Short Identifier=Plan1_subcritical
Geom File=g01
Flow File=f01
Subcritical Flow
K Sum by GR= 0
Std Step Tol= 0.003
Critical Tol= 0.003
Num of Std Step Trials= 20
Max Error Tol= 0.1
Flow Tol Ratio= 0.001
Split Flow NTrial= 30
Split Flow Tol= 0.006
Split Flow Ratio= 0.02
Log Output Level= 0
Friction Slope Method= 1
Unsteady Friction Slope Method= 2
Unsteady Bridges Friction Slope Method= 1
Parabolic Critical Depth
Global Vel Dist= 0 , 0 , 0
Global Log Level= 0
CheckData=True
Encroach Param=-1 ,0,0, 0
Computation Interval=1MIN
Output Interval=1HOUR
Instantaneous Interval=1HOUR
Mapping Interval=1HOUR
Computation Time Step Use Courant=        0
Computation Time Step Use Time Series=    0
Computation Time Step Count To Double=0
Computation Time Step Max Doubling=0
Computation Time Step Max Halving=0
Computation Time Step Residence Courant=0
Run HTab= 0
Run UNet= 0
Run Sediment= 0
Run PostProcess= 0
Run WQNet= 0
Run RASMapper=-1
UNET Theta= 1
UNET Theta Warmup= 1
UNET ZTol= 0.006
UNET ZSATol= 0.006
UNET MxIter= 20
UNET Max Iter WO Improvement= 0
UNET MaxInSteps= 0
UNET DtIC= 0
UNET DtMin= 0
UNET MaxCRTS= 20
UNET WFStab= 2
UNET SFStab= 1
UNET WFX= 1
UNET SFX= 1
UNET 1D Methodology=Finite Difference
UNET DSS MLevel= 4
UNET Pardiso=0
UNET DZMax Abort= 30
UNET Use Existing IB Tables=-1
UNET Froude Reduction=False
UNET Froude Limit= 0.8
UNET Froude Power= 4
UNET D1 Cores= 0
UNET D2 Coriolis=0
UNET D2 Cores= 0
UNET D2 Theta= 1
UNET D2 Theta Warmup= 1
UNET D2 Z Tol= 0.003
UNET D2 Volume Tol= 0.003
UNET D2 Max Iterations= 20
UNET D2 Equation= 0
UNET D2 RampUpFraction=0.1
UNET D2 TimeSlices= 1
UNET D2 BCVolumeCheck=0
UNET D1D2 MaxIter= 0
UNET D1D2 ZTol=0.003
UNET D1D2 QTol=0.1
UNET D1D2 MinQTol=0.03
Write IC File= 0
Write IC File at Fixed DateTime=0
Write IC File at Sim End=0
Echo Input=False
Echo Parameters=False
Echo Output=False
Write Detailed= 0
HDF Write Warmup=0
HDF Write Time Slices=0
HDF Flush=0
HDF Face Node Velocities=0
HDF Compression= 1
HDF Chunk Size= 1
HDF Spatial Parts= 1
HDF Use Max Rows=0
HDF Fixed Rows= 1
Calibration Method= 0
Calibration Iterations= 20
Calibration Max Change=0.05
Calibration Tolerance=0.2
Calibration Maximum=1.5
Calibration Minimum=0.5
Calibration Optimization Method= 1
WQ AD Non Conservative
WQ ULTIMATE=-1
WQ Max Comp Step=1HOUR
WQ Output Interval=15MIN
WQ Output Selected Increments= 0
WQ Output face flow=0
WQ Output face velocity=0
WQ Output face area=0
WQ Output face dispersion=0
WQ Output cell volume=0
WQ Output cell surface area=0
WQ Output cell continuity=0
WQ Output cumulative cell continuity=0
WQ Output face conc=0
WQ Output face dconc_dx=0
WQ Output face courant=0
WQ Output face peclet=0
WQ Output face adv mass=0
WQ Output face disp mass=0
WQ Output cell mass=0
WQ Output cell source sink temp=0
WQ Output nsm pathways=0
WQ Output nsm derived pathways=0
WQ Output MaxMinRange=-1
WQ Daily Max Min Mean=-1
WQ Daily Range=0
WQ Daily Time=0
WQ Create Restart=0
WQ Fixed Restart=0
WQ System Summary=0
WQ Write To DSS=0
WQ Use Fixed Temperature=0
Sorting and Armoring Iterations= 10
XS Update Threshold= 0.02
Bed Roughness Predictor= 0
Hydraulics Update Threshold= 0.02
Energy Slope Method= 1
Volume Change Method= 1
Sediment Retention Method= 0
XS Weighting Method= 0
Number of US Weighted Cross Sections= 1
Number of DS Weighted Cross Sections= 1
Upstream XS Weight=0
Main XS Weight=1
Downstream XS Weight=0
Number of DS XS's Weighted with US Boundary= 1
Upstream Boundary Weight= 1
Weight of XSs Associated with US Boundary= 0
Number of US XS's Weighted with DS Boundary= 1
Downstream Boundary Weight= 0.5
Weight of XSs Associated with DS Boundary= 0.5
Percentile Method= 0
Sediment Output Level= 4
Mass or Volume Output= 0
Output Increment Type= 1
Profile and TS Output Increment= 1
XS Output Flag= 0
XS Output Increment= 10
Write Gradation File= 0
Read Gradation Hotstart= 0
Write HDF5 File= 1
Write Binary Output= 1
Write DSS Sediment File= 0
SV Curve= 0
Specific Gage Flag= 0

--- SBHaddixRun.f01 (steady flow) ---

Flow Title=SBHaddixRun_flow
Program Version=5.05
Number of Profiles= 1
Profile Names=PF 1
River Rch & RM=SB Haddix Run,1               ,2834.64
   13.48
River Rch & RM=SB Haddix Run,1               ,2194.56
   15.57
River Rch & RM=SB Haddix Run,1               ,1554.48
   17.39
River Rch & RM=SB Haddix Run,1               ,1280.16
    19.2
River Rch & RM=SB Haddix Run,1               ,274.32
   20.88
Boundary for River Rch & Prof#=SB Haddix Run,1               , 1
Up Type= 2
Dn Type= 1
Dn Known WS=534
DSS Import GetInterval= 0
DSS Import GetPeak= 0
DSS Import FillOption= 0

--- SBHaddixRun.g01 (geometry) ---

Geom Title=SBHaddixRun_geometry
Program Version=5.05

River Reach=SB Haddix Run   ,1
Reach XY= 30
     608477.6703    4326537.1599     608490.3703    4326483.9785
     608550.2986    4326448.6566     608674.9176    4326454.6097
     608709.0489    4326439.9253     608824.7114     4326471.076
     608939.6337    4326454.2129     608983.2901    4326426.4316
609054.6226243854326436.93273594609083.172816547 4326465.4829281
609202.7020377644326459.72579764     609231.1784    4326429.1572
     609353.4732    4326460.0954     609395.5999     4326499.148
     609877.0544    4326532.3974     609939.6387    4326520.7353
     609991.3546    4326464.5316     610033.7707    4326449.6488
     610079.7918    4326460.9598     610215.9698    4326444.4894
     610282.8599    4326411.0857     610292.7817     4326433.906
     610310.6412    4326417.7003     610354.6282    4326431.2602
     610393.5991    4326396.7787     610413.4981    4326420.3461
      610465.092    4326400.1716     610644.5049    4326437.1049
     610856.0146    4326418.6925     611057.2915    4326470.3195

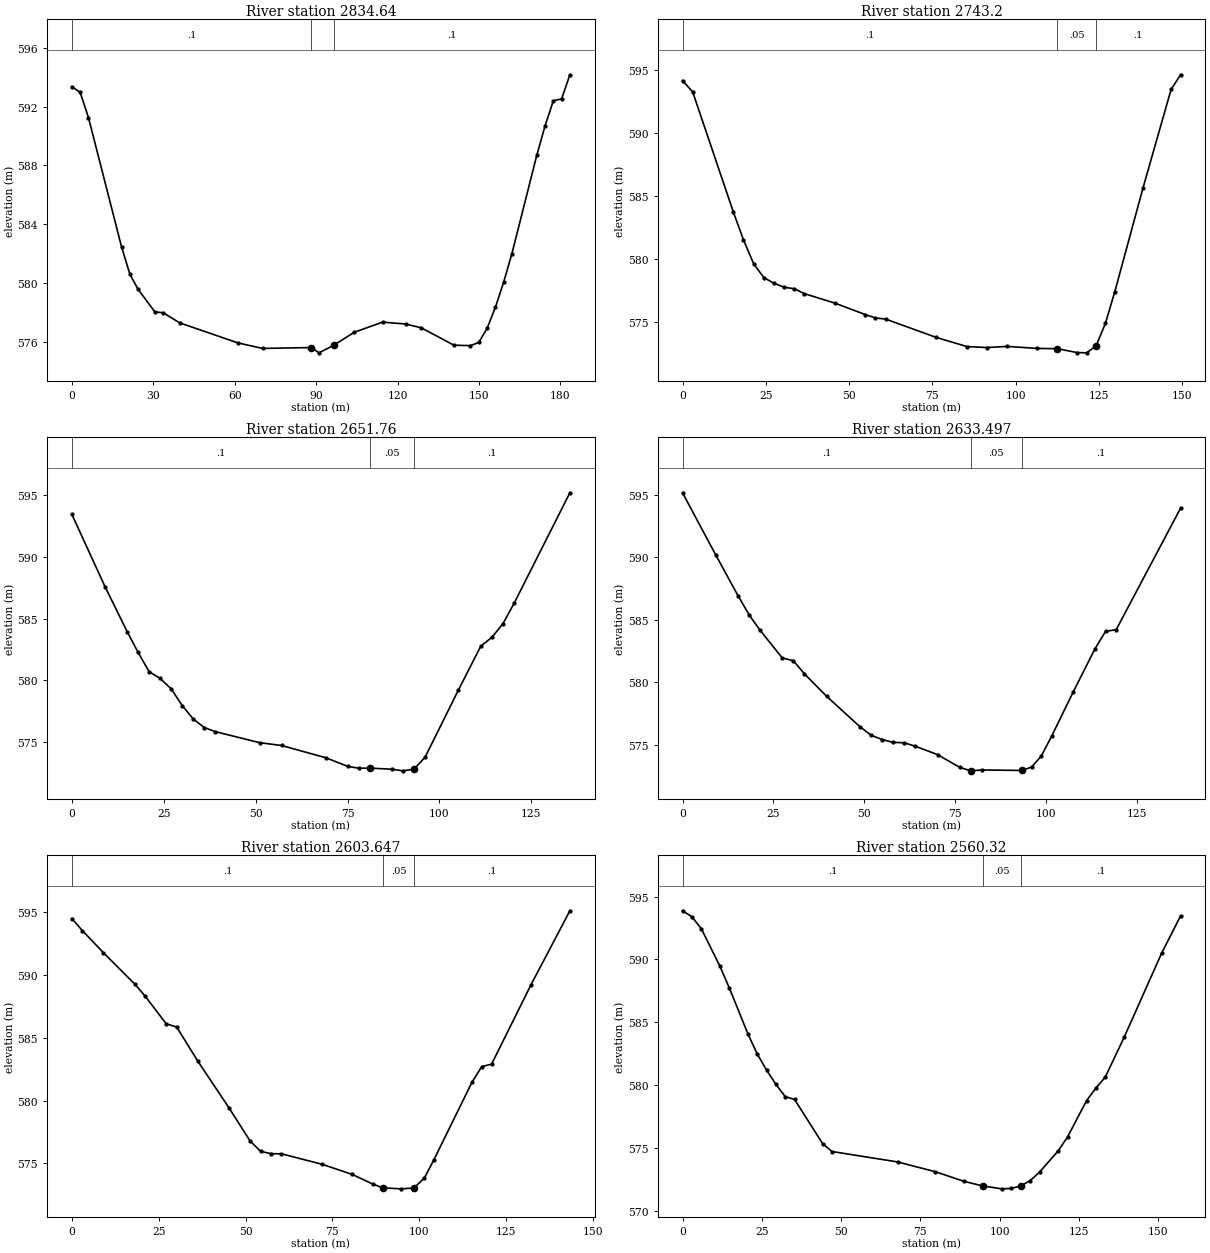
Type RM Length L Ch R = 1 ,2834.64 ,60.53,91.44,113.85
XS GIS Cut Line= 6
     608547.0989    4326559.6592      608518.433     4326495.499
     608491.0843    4326504.7731     608481.6029    4326504.8124
     608461.9973    4326493.1178     608440.4118     4326445.938
#Sta/Elev= 30
       0  593.35    3.06  592.96    6.11  591.25   18.33  582.43   21.39  580.58
   24.44  579.55   30.55  578.03   33.61  577.97   39.72  577.28   61.11  575.92
   70.27  575.54   88.27   575.6   91.03  575.24   96.54  575.76  104.03  576.64
  114.48  577.33  123.04   577.2  128.75  576.94  140.76  575.76  146.86  575.73
  149.91  575.95  152.97   576.9  156.02  578.33  159.07  580.04  162.12  581.99
  171.28  588.68  174.33  590.68  177.38  592.39  180.43  592.52  183.48  594.16
#Mann= 3 , 0 , 0
       0      .1       0   88.27     .05       0   96.54      .1       0
Bank Sta=88.27,96.54
XS Rating Curve= 0 ,0
Exp/Cntr=0.3,0.1

Type RM Length L Ch R = 1 ,2743.2  ,90.95,91.44,92.7
XS GIS Cut Line= 4
     608556.4613    4326558.1081     608552.6353    4326457.6329
     608552.8767    4326439.7678     608551.7775    4326408.7931
#Sta/Elev= 28
       0   594.2    3.05   593.3   15.23  583.78   18.28  581.56   21.33  579.66
   24.38  578.56   27.42  578.11   30.47  577.79   33.52  577.67   36.56  577.28
    45.7  576.53   54.84  575.62   57.89  575.35   60.94  575.26   76.17   573.8
   85.31  573.08   91.41     573    97.5  573.09   106.5  572.93  112.46  572.91
  118.41   572.6  121.23  572.58  124.05  573.12  126.87  574.91  129.69  577.43
  138.14  585.66  146.59   593.5  149.41  594.66
#Mann= 3 , 0 , 0
       0      .1       0  112.46     .05       0  124.05      .1       0
Bank Sta=112.46,124.05
XS Rating Curve= 0 ,0
Exp/Cntr=0.3,0.1

Type RM Length L Ch R = 1 ,2651.76 ,18.56,18.26,17.9
XS GIS Cut Line= 3
     608640.9326    4326541.4657     608644.3624    4326445.4301
     608650.0616    4326406.4458
#Sta/Elev= 27
       0  593.42    9.01  587.58   15.02  583.95   18.02  582.26   21.02   580.7
   24.02  580.15   27.03  579.31   30.03  577.96   33.03  576.87   36.04  576.18
   39.04  575.85   51.05  574.96   57.06  574.73   69.07  573.74   75.08  573.04
   78.08  572.89   81.08   572.9   87.09  572.81   90.09  572.68   93.09  572.82
    96.1  573.78  105.19  579.23  111.25  582.76  114.28  583.48  117.31  584.59
  120.34  586.24   135.5  595.17
#Mann= 3 , 0 , 0
       0      .1       0   81.08     .05       0   93.09      .1       0
Bank Sta=81.08,93.09
XS Rating Curve= 0 ,0
Exp/Cntr=0.3,0.1

Type RM Length L Ch R = 1 ,2633.497,33.23,29.85,24.93
XS GIS Cut Line= 4
     608663.0359    4326543.1162     608661.9776    4326457.6557
     608663.0359    4326444.4265     608662.7713    4326406.0618
#Sta/Elev= 28
       0  595.18    9.16  590.19   15.26  586.94   18.31  585.41   21.37  584.15
   27.47  581.94   30.52  581.72   33.58  580.66   39.68  578.86   48.84  576.43
   51.89  575.75   54.94   575.4      58  575.17   61.05  575.14    64.1  574.86
   70.21  574.19   76.31  573.17   79.36  572.89   82.41  572.96   93.43  572.92
   96.08  573.19   98.74  574.06  101.69  575.71  107.59  579.23  113.49  582.64
  116.45  584.07   119.4  584.21   137.1  593.94
#Mann= 3 , 0 , 0
       0      .1       0   79.36     .05       0   93.43      .1       0
Bank Sta=79.36,93.43
XS Rating Curve= 0 ,0
Exp/Cntr=0.3,0.1

Type RM Length L Ch R = 1 ,2603.647,31.42,43.33,49.76
XS GIS Cut Line= 6
     608690.8172    4326539.6766     608696.6381    4326473.5307
     608693.7277    4326456.5973     608687.9068    4326439.6639
      608685.261    4326429.0806     608683.6735    4326398.1243
#Sta/Elev= 26
       0   594.5    3.02  593.54    9.05  591.79   18.11  589.28   21.13  588.31
   27.16  586.12   30.18  585.86   36.22  583.16   45.27  579.41   51.31  576.79
   54.33  575.96   57.35  575.77   60.36  575.76   72.13  574.92   80.72  574.12
   86.57  573.36   89.55  573.05   94.87  572.97    98.5  573.04  101.49  573.83
  104.22  575.27  115.22  581.47  118.03  582.71  120.85   582.9  132.12  589.18
   143.4  595.12
#Mann= 3 , 0 , 0
       0      .1       0   89.55     .05       0    98.5      .1       0
Bank Sta=89.55,98.5
XS Rating Curve= 0 ,0
Exp/Cntr=0.3,0.1

Type RM Length L Ch R = 1 ,2560.32 ,46.9,43.68,41.78
XS GIS Cut Line= 5
     608710.3674    4326541.7153     608717.9347    4326483.3293
     608728.7164     4326455.568     608733.9256     4326438.397
     608753.3155    4326391.9131
#Sta/Elev= 30
       0  593.87    2.94   593.4    5.89  592.46   11.77  589.47   14.72  587.75
   20.61  584.08   23.55  582.48   26.49   581.2   29.44  580.06   32.38  579.09
   35.32  578.86   44.16  575.35    47.1  574.72   67.81  573.89   79.72  573.11
   88.66  572.35   94.64  571.98  100.62  571.75  103.61  571.78   106.6  571.98
  109.56   572.4  112.53  573.08  118.45  574.78  121.41   575.9  127.34  578.76
   130.3  579.77  133.26  580.64  139.19   583.8  151.04  590.51  156.97  593.45
#Mann= 3 , 0 , 0
       0      .1       0   94.64     .05       0   106.6      .1       0
Bank Sta=94.64,106.6
XS Rating Curve= 0 ,0
Exp/Cntr=0.3,0.1

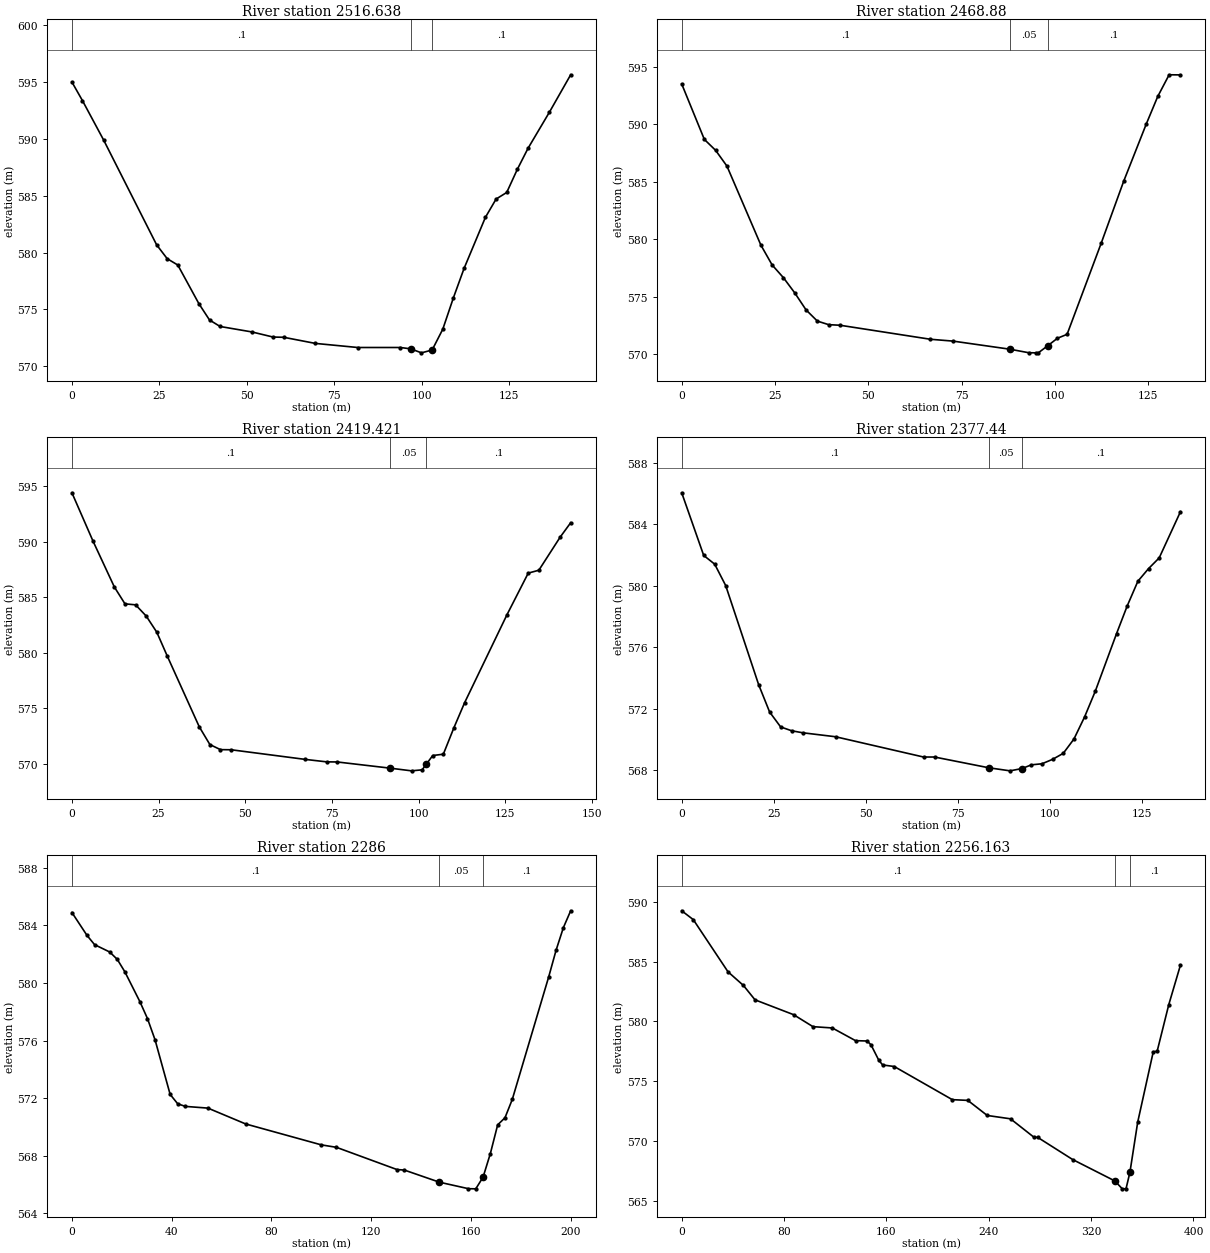
Type RM Length L Ch R = 1 ,2516.638,49.19,47.76,45.28
XS GIS Cut Line= 4
     608754.0528    4326560.5788     608769.3986    4326471.1494
     608770.9861    4326462.1536     608782.6278    4326421.1431
#Sta/Elev= 28
       0  595.02    3.02  593.38    9.07  589.91    24.2  580.69   27.22  579.47
   30.25  578.91   36.29   575.5   39.32  574.07   42.34   573.5   51.42  573.02
   57.47  572.57   60.49  572.55   69.56  572.01   81.66  571.65   93.86  571.65
   96.83  571.53   99.87  571.18  102.92  571.43  105.96  573.26  109.01  576.04
  112.05  578.62  118.14  583.11  121.19  584.72  124.23   585.3  127.28  587.35
  130.32  589.19  136.41  592.36   142.5  595.66
#Mann= 3 , 0 , 0
       0      .1       0   96.83     .05       0  102.92      .1       0
Bank Sta=96.83,102.92
XS Rating Curve= 0 ,0
Exp/Cntr=0.3,0.1

Type RM Length L Ch R = 1 ,2468.88 ,51.68,49.46,47.05
XS GIS Cut Line= 4
     608813.9238    4326566.5462     608816.3455    4326478.7702
     608818.8485    4326463.5782     608819.5968    4326433.2176
#Sta/Elev= 27
       0  593.49    6.06  588.67    9.08  587.72   12.11  586.35    21.2  579.48
   24.22  577.75   27.25  576.64   30.28  575.32   33.31  573.84   36.33  572.87
   39.36  572.56   42.39  572.51   66.61  571.29   72.67  571.13   87.81  570.43
   92.94  570.12   94.76  570.11   95.51  570.11   98.07  570.74  100.64  571.38
  103.21  571.72  112.32  579.62  118.39  585.05  124.47  590.05   127.5  592.41
  130.54  594.29  133.58  594.28
#Mann= 3 , 0 , 0
       0      .1       0   87.81     .05       0   98.07      .1       0
Bank Sta=87.81,98.07
XS Rating Curve= 0 ,0
Exp/Cntr=0.3,0.1

Type RM Length L Ch R = 1 ,2419.421,44.86,41.98,40.23
XS GIS Cut Line= 2
     608871.7926    4326565.0767     608864.3842    4326421.4077
#Sta/Elev= 28
       0  594.42    6.12  590.04   12.24  585.93    15.3  584.41   18.37  584.32
   21.43  583.31   24.49  581.85   27.55  579.67   36.73  573.33   39.79  571.73
   42.85  571.27   45.91  571.26   67.34  570.39   73.46  570.17   76.52  570.16
   91.83   569.6   97.95  569.36  101.01  569.45  102.27  569.98  104.07  570.74
  107.13  570.86  110.19  573.25  113.25  575.49  125.49  583.43  131.62  587.18
  134.68  587.44   140.8  590.41  143.86  591.72
#Mann= 3 , 0 , 0
       0      .1       0   91.83     .05       0  102.27      .1       0
Bank Sta=91.83,102.27
XS Rating Curve= 0 ,0
Exp/Cntr=0.3,0.1

Type RM Length L Ch R = 1 ,2377.44 ,76.51,91.44,105.06
XS GIS Cut Line= 4
     608922.7141    4326550.7327     608911.2541    4326473.9583
     608906.6768    4326454.2559      608900.767    4326417.0903
#Sta/Elev= 28
       0  586.06    5.97  581.98    8.96  581.41   11.94  580.02    20.9  573.56
   23.88  571.78   26.87  570.81   29.86  570.56   32.84  570.43    41.8  570.17
   65.68  568.85   68.67  568.85    83.4  568.15   89.18  567.95   92.44   568.1
   94.96  568.34   97.85  568.41  100.75   568.7  103.64  569.09  106.54  570.02
  109.43  571.46  112.33  573.13  118.12  576.89  121.01  578.69  123.91   580.3
   126.8  581.12   129.7  581.82  135.48  584.83
#Mann= 3 , 0 , 0
       0      .1       0    83.4     .05       0   92.44      .1       0
Bank Sta=83.4,92.44
XS Rating Curve= 0 ,0
Exp/Cntr=0.3,0.1

Type RM Length L Ch R = 1 ,2286    ,33.08,29.84,21.13
XS GIS Cut Line= 5
     608989.5002    4326578.2734     608982.9033    4326439.0007
     608990.4559    4326428.0493      608995.298    4326423.9986
     609020.8098    4326391.9131
#Sta/Elev= 30
       0  584.88    6.06  583.29    9.09  582.65   15.16  582.14   18.19  581.63
   21.22  580.77   27.28  578.69   30.31  577.52   33.34  576.05    39.4  572.26
   42.43  571.61   45.47  571.43   54.56  571.31   69.71  570.21  100.03  568.76
  106.09  568.59  130.34  567.05  133.37  567.01  147.41  566.17  159.05  565.72
  161.97  565.71   164.9  566.52  167.83  568.16  170.76  570.15  173.69  570.64
  176.61  571.91  191.25  580.43  194.18  582.26  197.11  583.83  200.04     585
#Mann= 3 , 0 , 0
       0      .1       0  147.41     .05       0   164.9      .1       0
Bank Sta=147.41,164.9
XS Rating Curve= 0 ,0
Exp/Cntr=0.3,0.1

Type RM Length L Ch R = 1 ,2256.163,40.52,37.21,32.06
XS GIS Cut Line= 6
     609024.9866    4326777.2465     609035.7023    4326684.3776
      609020.621    4326558.1711     609016.2554    4326449.0302
     609016.6523    4326431.5677     609030.9398    4326391.4832
#Sta/Elev= 30
       0  589.24    9.05   588.5   36.19  584.14   48.25     583    57.3   581.8
   87.45  580.56  102.56  579.56   117.7  579.45  135.85  578.39  144.93  578.36
  147.96  578.04  154.01  576.76  157.04  576.36  166.12  576.23  211.51  573.46
  223.62   573.4  238.79  572.14     257  571.86   275.2  570.33  278.24  570.31
  305.54  568.46  338.55  566.67  344.37  566.01  347.28  566.02  350.32  567.39
   356.4  571.58  368.56  577.46   371.6   577.5  380.72  581.41  389.84  584.71
#Mann= 3 , 0 , 0
       0      .1       0  338.55     .05       0  350.32      .1       0
Bank Sta=338.55,350.32
XS Rating Curve= 0 ,0
Exp/Cntr=0.3,0.1

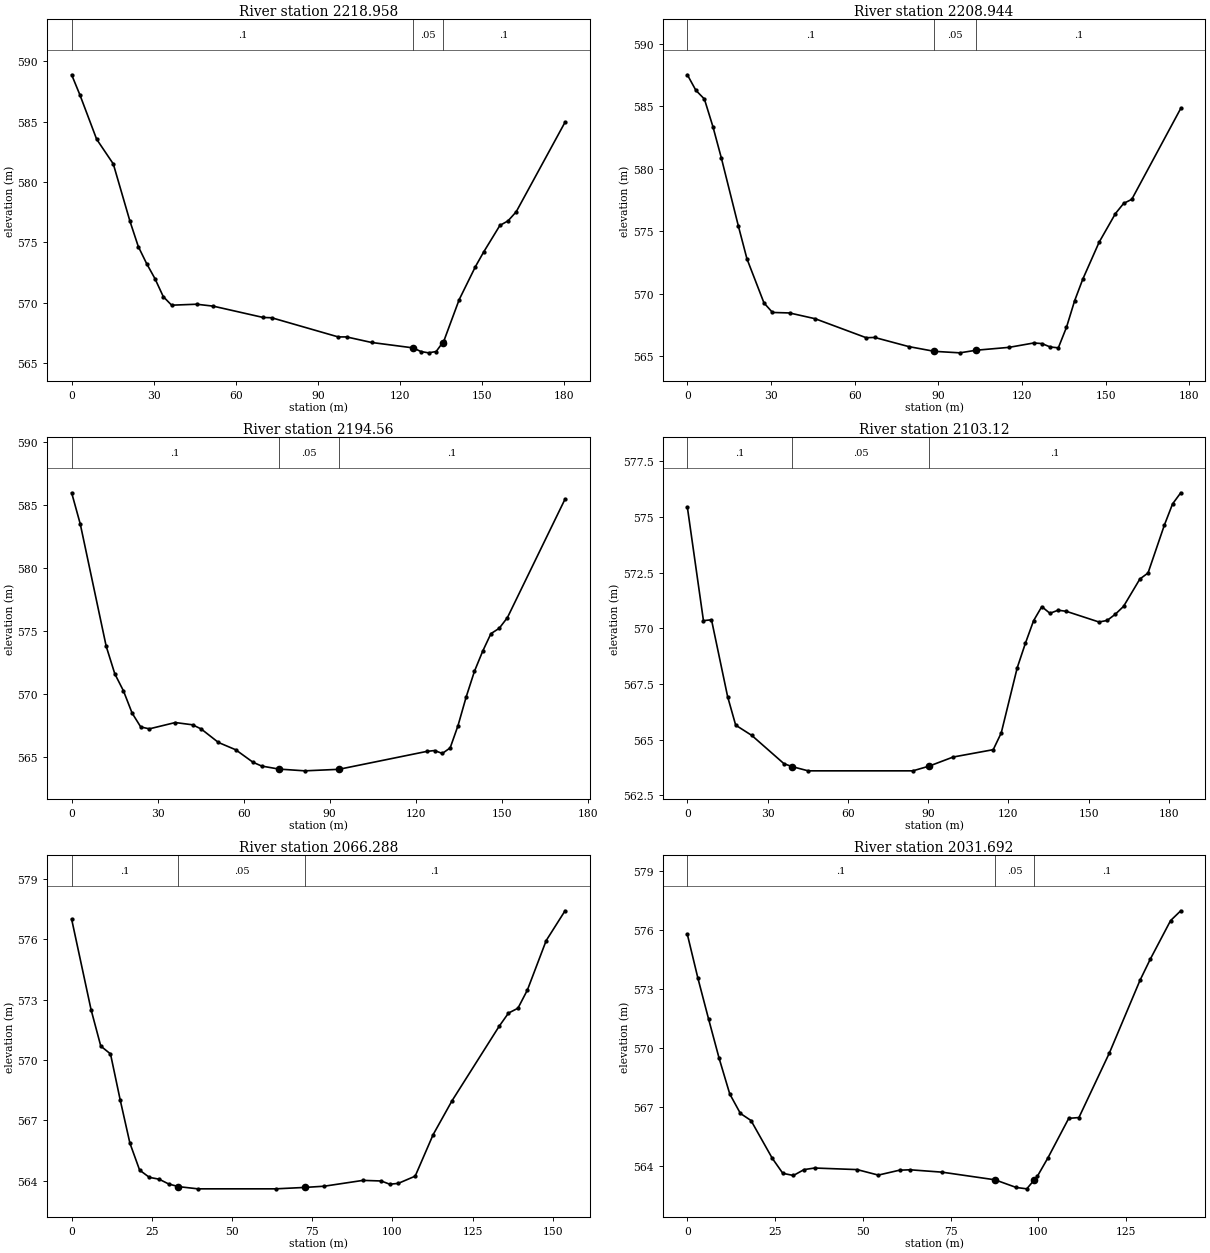
Type RM Length L Ch R = 1 ,2218.958,16.87,10.01,9.82
XS GIS Cut Line= 4
     609067.8492    4326566.9023     609055.5461    4326442.6802
     609049.7252     4326426.911     609039.1419    4326389.6841
#Sta/Elev= 30
       0  588.88    3.04   587.2    9.13  583.54   15.22  581.49   21.31  576.74
   24.36  574.64    27.4  573.23   30.45  571.98   33.49  570.49   36.54  569.78
   45.67  569.86   51.76   569.7   70.03  568.76   73.07  568.74   97.43  567.15
  100.47  567.15  109.61  566.69  124.83  566.24  127.63  565.94  130.43  565.83
  133.23  565.94  135.56  566.66  136.04  566.81  141.64  570.24  147.59  572.98
  150.57  574.18  156.52  576.39   159.5  576.77  162.48  577.52  180.34  584.95
#Mann= 3 , 0 , 0
       0      .1       0  124.83     .05       0  135.56      .1       0
Bank Sta=124.83,135.56
XS Rating Curve= 0 ,0
Exp/Cntr=0.3,0.1

Type RM Length L Ch R = 1 ,2208.944,17.13,14.38,12.61
XS GIS Cut Line= 4
     609088.0667     4326558.224     609077.2188    4326461.1217
     609064.5188    4326437.8383     609045.7333    4326388.6257
#Sta/Elev= 30
       0  587.51    3.05  586.27    6.11  585.57    9.16  583.37   12.21  580.84
   18.32  575.39   21.37  572.79   27.48  569.26   30.53   568.5   36.64  568.46
    45.8     568   64.12  566.48   67.17   566.5   79.39  565.77   88.55  565.39
   97.71  565.27   103.6  565.48  115.39  565.71  124.23  566.06  127.15  566.01
  130.08  565.74  133.01  565.67  135.93  567.31  138.86  569.44  141.79  571.17
  147.64  574.12  153.49  576.41  156.42  577.22  159.35  577.55   176.9  584.82
#Mann= 3 , 0 , 0
       0      .1       0   88.55     .05       0   103.6      .1       0
Bank Sta=88.55,103.6
XS Rating Curve= 0 ,0
Exp/Cntr=0.3,0.1

Type RM Length L Ch R = 1 ,2194.56 ,71.2,91.44,100.64
XS GIS Cut Line= 5
     609106.5569    4326546.7971     609094.6658    4326457.2038
     609083.7701    4326437.4464     609071.2468    4326419.5559
     609054.9663    4326385.9352
#Sta/Elev= 30
       0  585.98    3.01   583.5   12.05  573.81   15.06  571.62   18.08  570.27
   21.09  568.51    24.1  567.41   27.11  567.26   36.15  567.76   42.18  567.58
   45.19  567.25   51.21  566.18   57.24   565.6   63.27  564.61   66.28  564.31
    72.3  564.07   81.34  563.93    93.2  564.05  123.86  565.47  126.59  565.54
  129.32  565.31  132.05  565.75  134.78  567.51  137.65   569.8  140.53  571.83
   143.4  573.42  146.27  574.81  149.15  575.23  152.02  576.08  172.13  585.48
#Mann= 3 , 0 , 0
       0      .1       0    72.3     .05       0    93.2      .1       0
Bank Sta=72.3,93.2
XS Rating Curve= 0 ,0
Exp/Cntr=0.3,0.1

Type RM Length L Ch R = 1 ,2103.12 ,36.77,36.83,35.63
XS GIS Cut Line= 4
     609140.4546    4326525.3162     609159.4894    4326424.7205
     609165.7892    4326404.7417     609188.6089     4326348.045
#Sta/Elev= 30
       0  575.44    6.02  570.34    9.03  570.38   15.06  566.93   18.07  565.65
   24.09  565.19   36.13  563.92   39.15  563.79   45.17   563.6   84.31   563.6
   90.34  563.81   99.37  564.22  114.35  564.55  117.34   565.3  123.33  568.23
  126.39  569.33  129.44  570.34   132.5  570.97  135.55  570.67  138.61  570.81
  141.66  570.76  153.89  570.28  156.94  570.35     160  570.63  163.06  570.98
  169.17  572.21  172.22  572.48  178.33  574.63  181.39  575.58  184.45  576.08
#Mann= 3 , 0 , 0
       0      .1       0   39.15     .05       0   90.34      .1       0
Bank Sta=39.15,90.34
XS Rating Curve= 0 ,0
Exp/Cntr=0.3,0.1

Type RM Length L Ch R = 1 ,2066.288,35.32,34.6,33.68
XS GIS Cut Line= 4
     609173.8096    4326521.3421     609196.9606    4326430.3914
     609200.2679    4326414.8471     609212.5049    4326372.5137
#Sta/Elev= 28
       0  576.99    6.05   572.5    9.08  570.69   12.11   570.3   15.14  568.01
   18.16  565.87   21.19  564.53   24.22  564.17   27.25  564.08   30.27  563.84
    33.3  563.71   39.36   563.6   63.58   563.6   72.66  563.67   78.71  563.73
   90.82  564.02    96.5  563.99   99.15  563.83   101.8  563.87  107.09  564.23
  112.68  566.29  118.56  567.97  133.25  571.67  136.18  572.33  139.12  572.57
  142.06  573.47  147.93  575.93  153.81  577.41
#Mann= 3 , 0 , 0
       0      .1       0    33.3     .05       0   72.66      .1       0
Bank Sta=33.3,72.66
XS Rating Curve= 0 ,0
Exp/Cntr=0.3,0.1

Type RM Length L Ch R = 1 ,2031.692,23.7,20.01,19.54
XS GIS Cut Line= 4
     609210.8513    4326523.6572     609231.0258    4326438.3289
     609234.0024    4326420.4695     609236.6482    4326385.7429
#Sta/Elev= 30
       0  575.78    3.02  573.54    6.05  571.47    9.07  569.46   12.09  567.65
   15.12  566.66   18.14   566.3   24.19  564.38   27.21  563.61   30.23   563.5
   33.26   563.8   36.28  563.88   48.38   563.8   54.42  563.52   60.47  563.77
   63.49  563.79   72.56  563.67   87.68  563.28   93.72  562.89   96.73  562.82
   98.75  563.25   99.75  563.46  102.77   564.4  108.69  566.41  111.59  566.45
   120.3  569.75     129  573.44  131.91  574.51  137.71  576.48  140.61  576.98
#Mann= 3 , 0 , 0
       0      .1       0   87.68     .05       0   98.75      .1       0
Bank Sta=87.68,98.75
XS Rating Curve= 0 ,0
Exp/Cntr=0.3,0.1

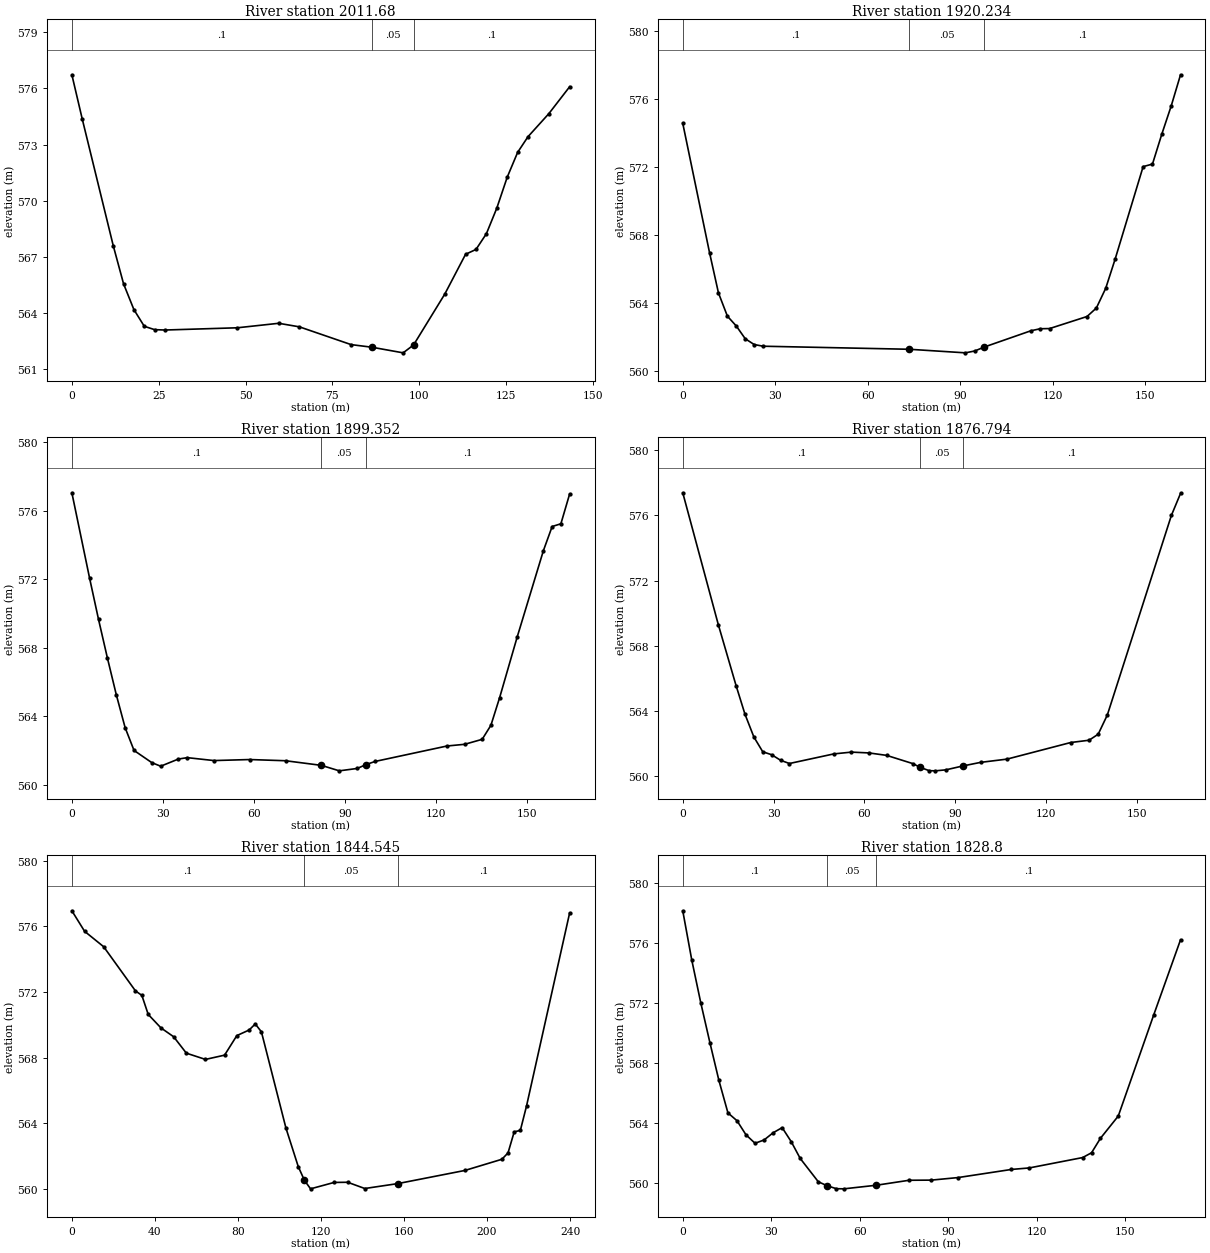
Type RM Length L Ch R = 1 ,2011.68 ,80.73,91.45,96.31
XS GIS Cut Line= 3
     609245.6116    4326528.4654     609250.6422    4326448.2544
     609257.1845     4326385.704
#Sta/Elev= 25
       0  576.73    2.98  574.37   11.91  567.59   14.88  565.55   17.86  564.17
   20.84  563.28   23.81   563.1   26.79  563.08   47.63   563.2   59.53  563.44
   65.49  563.25   80.37   562.3   86.36  562.16   95.34  561.86   98.34  562.28
  107.32     565  113.31  567.13  116.31  567.39   119.3  568.23   122.3   569.6
  125.29  571.25  128.29  572.58  131.28  573.42  137.27  574.65  143.26  576.09
#Mann= 3 , 0 , 0
       0      .1       0   86.36     .05       0   98.34      .1       0
Bank Sta=86.36,98.34
XS Rating Curve= 0 ,0
Exp/Cntr=0.3,0.1

Type RM Length L Ch R = 1 ,1920.234,20.23,20.88,21.26
XS GIS Cut Line= 3
     609314.7578    4326541.7307     609320.9036    4326492.8931
     609369.1874    4326391.5691
#Sta/Elev= 24
       0  574.57    8.69  566.95   11.58  564.58   14.48  563.21   17.37  562.63
   20.27  561.88   23.16  561.54   26.06  561.44   73.49  561.26   91.69  561.05
   94.73  561.16   97.76  561.39  112.93  562.35  115.96  562.47  118.99  562.48
  131.13  563.19  134.16  563.69  137.19  564.85  140.23  566.56  149.33  572.02
  152.36  572.17   155.4  573.94  158.43  575.59  161.46  577.43
#Mann= 3 , 0 , 0
       0      .1       0   73.49     .05       0   97.76      .1       0
Bank Sta=73.49,97.76
XS Rating Curve= 0 ,0
Exp/Cntr=0.3,0.1

Type RM Length L Ch R = 1 ,1899.352,20.57,22.56,24.11
XS GIS Cut Line= 4
     609330.1279    4326546.2284     609342.0342    4326494.9653
     609375.4379      4326429.15     609386.6827    4326393.4312
#Sta/Elev= 29
       0  577.05    5.85  572.05    8.77  569.66    11.7   567.4   14.62  565.26
   17.54  563.33   20.47     562   26.31  561.29   29.24  561.08   35.09   561.5
   38.01  561.58   46.78  561.41   58.53  561.47   70.34   561.4   82.15  561.13
   88.05  560.81   93.96  560.95   96.91  561.18   99.86  561.36  123.48  562.26
  129.32  562.36  135.08  562.65  137.96  563.47  140.84  565.09   146.6  568.62
  155.24  573.67  158.12  575.08     161  575.24  163.88  576.98
#Mann= 3 , 0 , 0
       0      .1       0   82.15     .05       0   96.91      .1       0
Bank Sta=82.15,96.91
XS Rating Curve= 0 ,0
Exp/Cntr=0.3,0.1

Type RM Length L Ch R = 1 ,1876.794,34.66,32.25,29.76
XS GIS Cut Line= 6
     609349.4271    4326548.7927     609360.6719    4326503.1519
     609372.9089    4326480.0009     609383.1615    4326467.1024
      609392.422    4326448.9123     609403.6668    4326395.6648
#Sta/Elev= 27
       0  577.39   11.75  569.29   17.63  565.54   20.56  563.79    23.5  562.39
   26.44  561.48   29.38   561.3   32.32  560.96   35.25  560.76   49.92  561.35
   55.73  561.46   61.55  561.41   67.37  561.26   75.94  560.76   78.53  560.52
   81.43  560.32   83.45  560.31   86.92  560.37   92.58  560.61   98.42  560.83
  107.16  561.03  128.22  562.05  134.27  562.19  137.29  562.56  140.31  563.74
  161.48     576   164.5  577.35
#Mann= 3 , 0 , 0
       0      .1       0   78.53     .05       0   92.58      .1       0
Bank Sta=78.53,92.58
XS Rating Curve= 0 ,0
Exp/Cntr=0.3,0.1

Type RM Length L Ch R = 1 ,1844.545,18.28,15.75,7.5
XS GIS Cut Line= 6
     609346.4593    4326618.6351     609384.1625    4326555.4657
      609394.349    4326497.2109     609406.2553    4326479.4309
     609412.7641    4326474.1921      609423.063    4326397.7307
#Sta/Elev= 30
       0  576.94    6.13  575.69   15.33  574.75   30.65  572.06   33.72  571.79
   36.78  570.63   42.91  569.81   49.04  569.27   55.17  568.27   64.37  567.89
   73.57  568.15   79.48  569.34    85.4  569.68   88.36  570.05   91.32  569.57
  103.16   563.7  109.08  561.36  112.04  560.53     115  560.01  126.35   560.4
  132.88  560.41  141.13  560.03  157.09  560.33  189.37  561.13  207.18  561.81
  210.14   562.2  213.11  563.48  216.08  563.57  219.04  565.05  239.82  576.81
#Mann= 3 , 0 , 0
       0      .1       0  112.04     .05       0  157.09      .1       0
Bank Sta=112.04,157.09
XS Rating Curve= 0 ,0
Exp/Cntr=0.3,0.1

Type RM Length L Ch R = 1 ,1828.8  ,89.86,91.44,93.93
XS GIS Cut Line= 6
     609409.4303    4326563.1205     609411.2205    4326511.0885
     609410.4696    4326493.3904     609408.8393    4326486.7468
     609414.9247    4326482.2489     609427.3788    4326398.7498
#Sta/Elev= 30
       0  578.12    3.06  574.84    6.13  571.98    9.19  569.36   12.25  566.84
   15.31  564.68   18.38  564.16   21.44  563.22    24.5  562.66   27.56  562.88
   30.63  563.36   33.69   563.7   36.75  562.77   39.81  561.65   45.94   560.1
      49  559.83   52.06  559.64   54.59  559.63   65.62  559.87    76.7   560.2
   84.27  560.21   93.31  560.38   111.4  560.92  117.43  561.02  135.52  561.71
  138.54  562.03  141.55  562.99  147.59  564.47  159.65  571.22  168.69  576.19
#Mann= 3 , 0 , 0
       0      .1       0      49     .05       0   65.62      .1       0
Bank Sta=49,65.62
XS Rating Curve= 0 ,0
Exp/Cntr=0.3,0.1

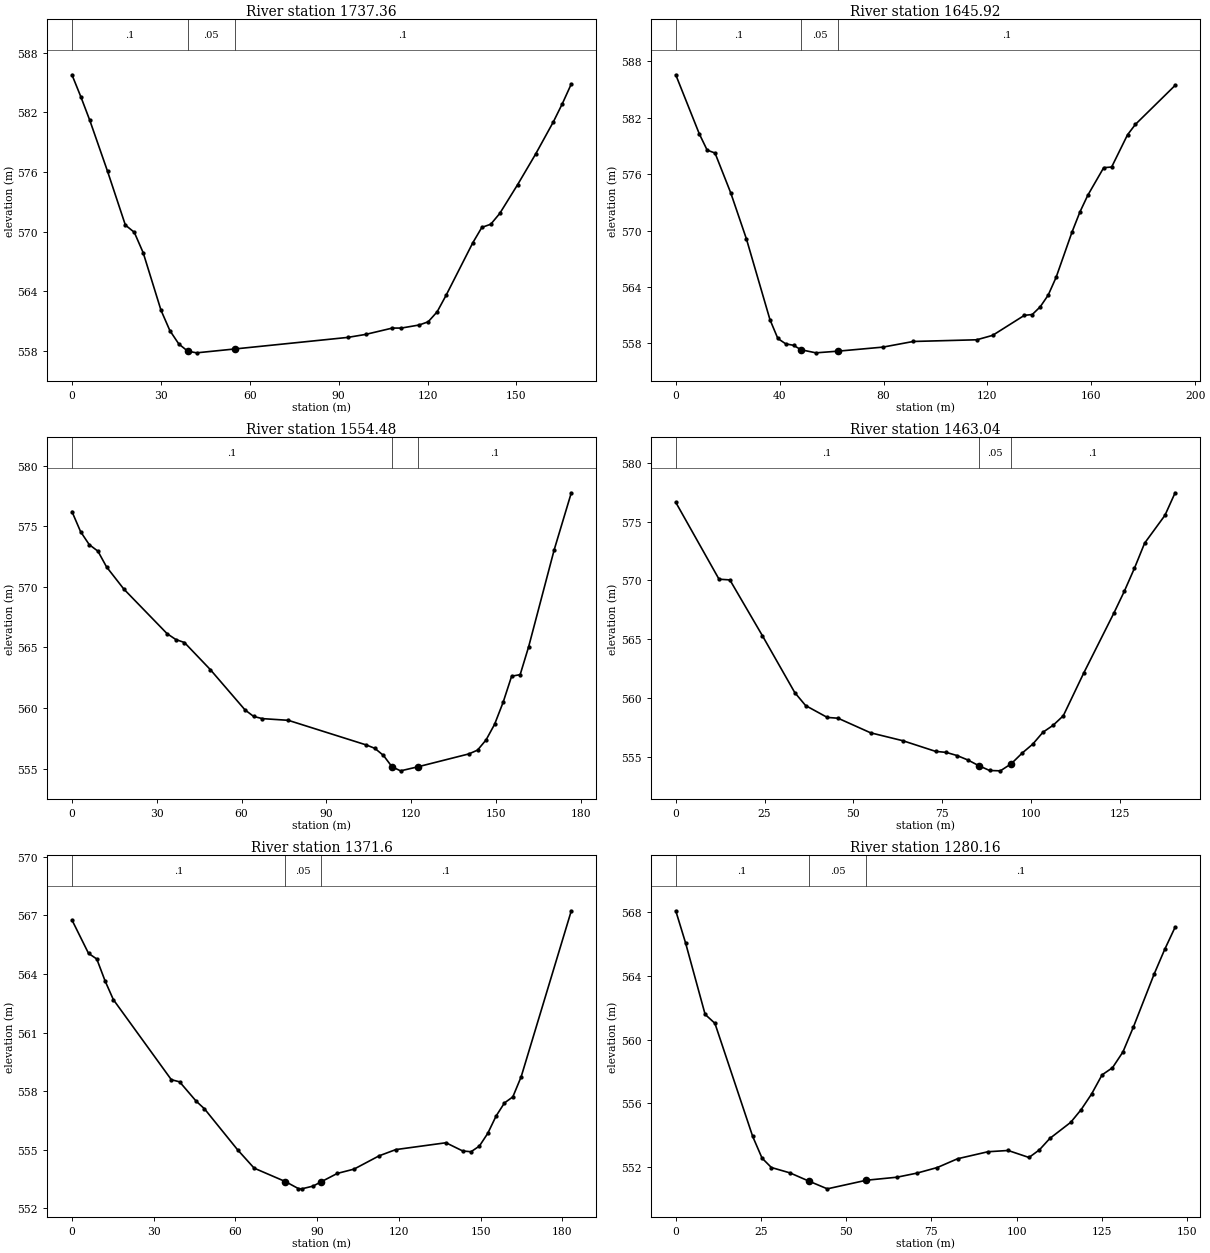
Type RM Length L Ch R = 1 ,1737.36 ,88.63,91.44,95.66
XS GIS Cut Line= 4
     609500.0661    4326553.5107     609501.3164    4326499.4424
     609503.4941    4326487.8713     609505.6006    4326385.2494
#Sta/Elev= 30
       0  585.77       3  583.56    6.01   581.2   12.02  576.06   18.03  570.66
   21.03  569.94   24.04  567.88   30.05   562.1   33.05  560.05   36.06  558.71
   39.06  557.99   42.06  557.82   54.96  558.21   93.03  559.37   99.07  559.67
  108.12  560.31  111.14  560.31  117.18  560.62   120.2  560.94  123.22  561.94
  126.24   563.6  135.29   568.9  138.31  570.43  141.33  570.75  144.35  571.83
  150.39  574.73  156.42  577.78  162.46  581.05  165.48  582.87   168.5  584.85
#Mann= 3 , 0 , 0
       0      .1       0   39.06     .05       0   54.96      .1       0
Bank Sta=39.06,54.96
XS Rating Curve= 0 ,0
Exp/Cntr=0.3,0.1

Type RM Length L Ch R = 1 ,1645.92 ,93.28,91.44,85
XS GIS Cut Line= 4
     609583.7305    4326564.6368     609589.5585    4326519.6604
     609602.8247    4326478.7085     609605.0911    4326374.8518
#Sta/Elev= 30
       0  586.58    9.07  580.29   12.09  578.56   15.12  578.25   21.16  574.02
   27.21  569.11   36.28  560.51   39.31  558.51   42.33  557.94   45.35  557.78
   48.22  557.31   53.96  556.98   62.57  557.16   79.79  557.59   91.45  558.19
   115.9  558.37  122.01  558.84  134.23  560.97  137.28  561.06  140.34  561.88
   143.4  563.12  146.45  565.01  152.56  569.82  155.62  571.97  158.67  573.76
  164.78  576.69  167.84  576.76  173.95  580.19     177   581.3  192.28  585.45
#Mann= 3 , 0 , 0
       0      .1       0   48.22     .05       0   62.57      .1       0
Bank Sta=48.22,62.57
XS Rating Curve= 0 ,0
Exp/Cntr=0.3,0.1

Type RM Length L Ch R = 1 ,1554.48 ,89.97,91.44,91.48
XS GIS Cut Line= 4
     609677.3614    4326637.9893     609682.1501    4326527.8579
     609681.9716    4326509.6542     609685.4313    4326461.5118
#Sta/Elev= 30
       0  576.22    3.06  574.56    6.12  573.49    9.19  572.95   12.25  571.65
   18.37  569.82   33.68  566.14   36.75  565.66   39.81  565.41   48.99  563.17
   61.24  559.85    64.3  559.31   67.37  559.13   76.55  558.99  104.11  556.96
  107.17  556.68  110.24  556.09  113.27  555.15   116.3  554.82  122.37  555.15
  140.51  556.22  143.52  556.53  146.54  557.37  149.56  558.66  152.57  560.47
  155.59  562.63  158.61  562.76  161.62  565.07  170.67  573.08  176.71  577.77
#Mann= 3 , 0 , 0
       0      .1       0  113.27     .05       0  122.37      .1       0
Bank Sta=113.27,122.37
XS Rating Curve= 0 ,0
Exp/Cntr=0.3,0.1

Type RM Length L Ch R = 1 ,1463.04 ,89.15,91.44,92.06
XS GIS Cut Line= 4
     609766.1344    4326605.3537     609772.3493    4326523.3432
     609773.2219    4326505.1097     609772.4302    4326465.0664
#Sta/Elev= 30
       0  576.66   12.18  570.11   15.23  570.05   24.37  565.31   33.51  560.45
   36.55  559.35   42.65  558.34   45.69  558.27   54.83  557.03   63.97  556.35
   73.11  555.45   76.15  555.36    79.2  555.09   82.25  554.71   85.29  554.23
   88.33  553.82   91.37  553.79   94.42  554.39   97.46  555.29   100.5  556.07
  103.36  557.08  106.22  557.67  109.08  558.48   114.8   562.1  123.39  567.27
  126.25  569.08  129.11  571.05  131.97  573.18  137.69  575.55  140.55  577.47
#Mann= 3 , 0 , 0
       0      .1       0   85.29     .05       0   94.42      .1       0
Bank Sta=85.29,94.42
XS Rating Curve= 0 ,0
Exp/Cntr=0.3,0.1

Type RM Length L Ch R = 1 ,1371.6  ,109.65,91.44,65.76
XS GIS Cut Line= 5
     609846.9597    4326617.2194     609859.5945    4326542.2702
     609861.6975    4326532.9557     609862.7107    4326521.1347
     609866.8035     4326435.318
#Sta/Elev= 30
       0  566.77    6.08  565.06    9.12  564.77   12.16  563.65    15.2  562.69
   36.48  558.59   39.52  558.48    45.6  557.49   48.64   557.1   60.81     555
   66.89  554.06   78.39  553.37   83.17  553.01   84.36     553   88.52  553.14
   91.49  553.36   97.42  553.79  103.56  554.01  112.76  554.69   118.9  555.01
  137.31  555.36  143.45  554.94  146.51   554.9  149.58  555.19  152.65  555.84
  155.72  556.73  158.79   557.4  161.86  557.71  164.92  558.74  183.33  567.24
#Mann= 3 , 0 , 0
       0      .1       0   78.39     .05       0   91.49      .1       0
Bank Sta=78.39,91.49
XS Rating Curve= 0 ,0
Exp/Cntr=0.3,0.1

Type RM Length L Ch R = 1 ,1280.16 ,74.43,91.44,104.43
XS GIS Cut Line= 6
     609981.8975    4326545.1203     609975.2639    4326532.3827
     609957.1488    4326515.6626     609932.7718    4326507.0958
     609911.7638    4326482.1118     609898.0571    4326435.0772
#Sta/Elev= 30
       0  568.09    2.87  566.08    8.62  561.58   11.49  561.02   22.58  553.91
   25.32  552.55   28.06  551.96   33.54  551.62   39.01  551.11   44.47  550.62
    55.9  551.16   64.88  551.35   70.81  551.61   76.75  551.96   82.68  552.51
   91.58  552.95   97.52  553.03  103.64  552.59   106.7  553.07  109.77  553.79
  115.89   554.8  118.95   555.6  122.01  556.58  125.08  557.78  128.14  558.23
   131.2  559.22  134.26  560.78  140.39  564.13  143.45  565.66  146.51  567.06
#Mann= 3 , 0 , 0
       0      .1       0   39.01     .05       0    55.9      .1       0
Bank Sta=39.01,55.9
XS Rating Curve= 0 ,0
Exp/Cntr=0.3,0.1