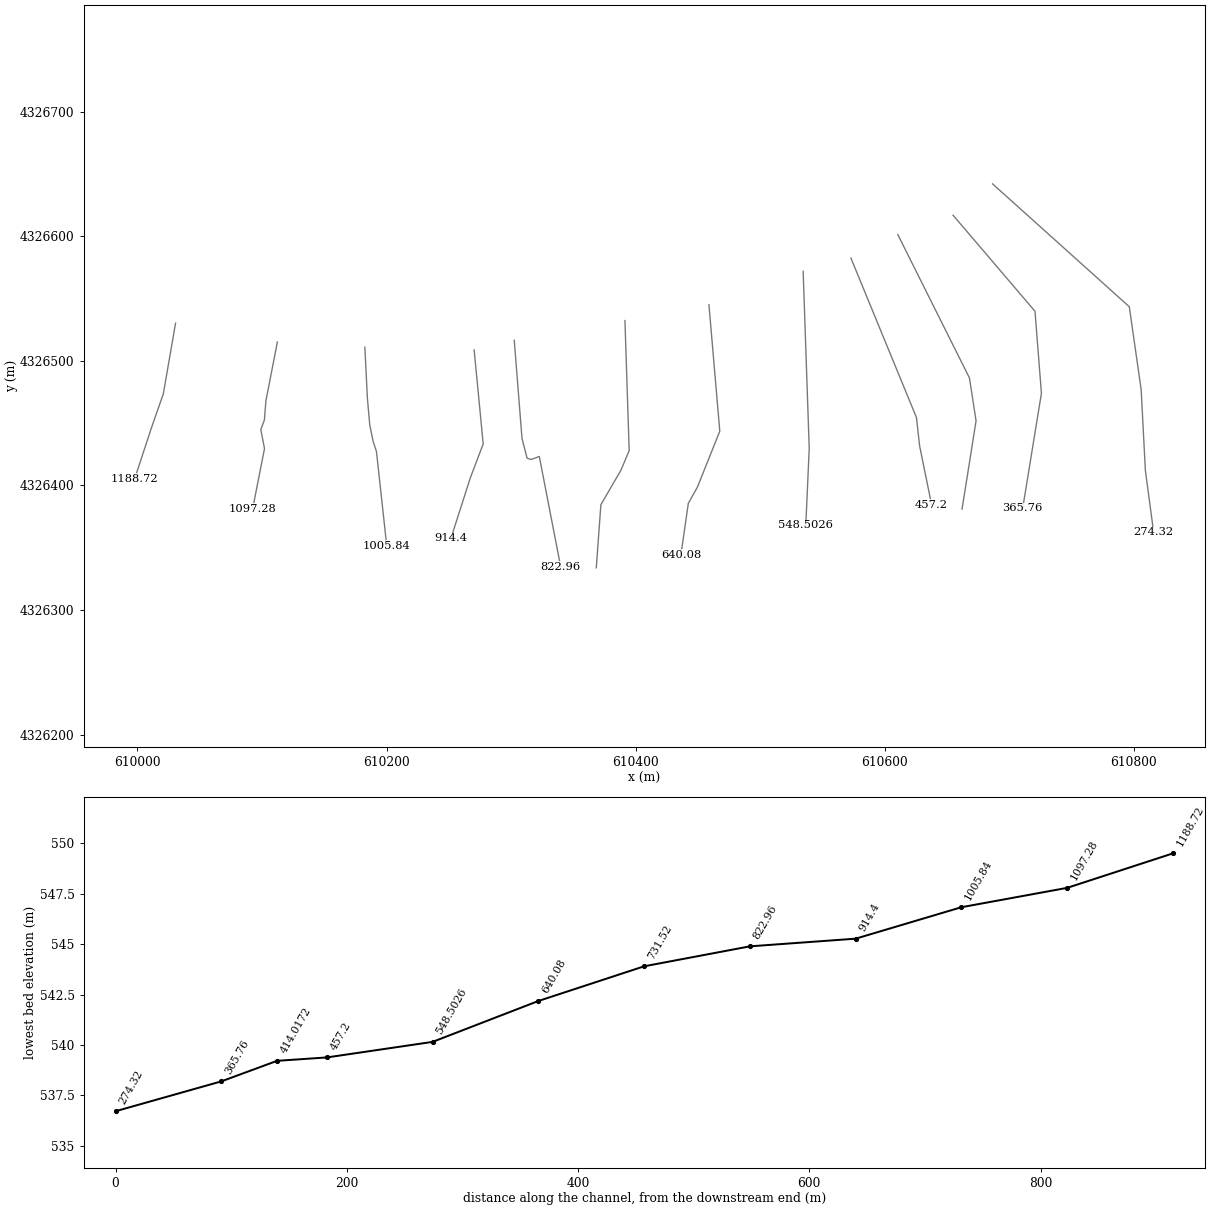
HEC-RAS study SBHaddixRun.prj: SBHaddixRun

--- SBHaddixRun.g01 (geometry) --- (continued)

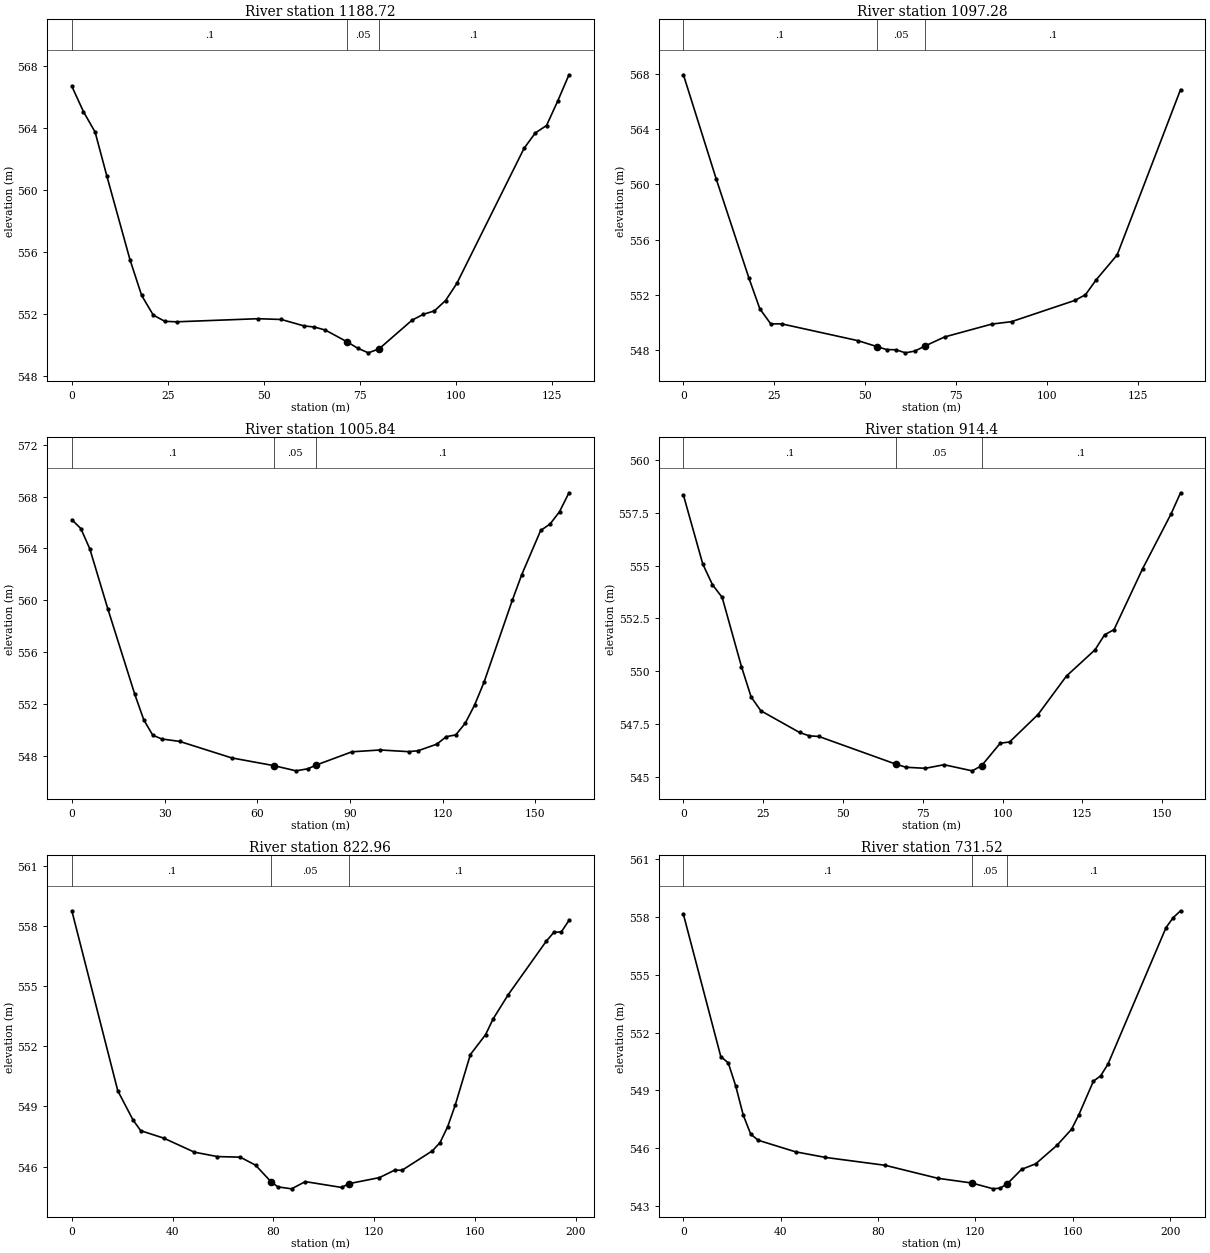
Type RM Length L Ch R = 1 ,1188.72 ,82.98,91.44,92.64
XS GIS Cut Line= 4
     610030.5827    4326530.1598      610020.757    4326473.4877
     610011.4759    4326447.0365     609997.7875    4326405.4667
#Sta/Elev= 28
       0  566.68    3.03  565.04    6.05  563.73    9.08  560.92   15.14  555.49
   18.16   553.2   21.19  551.93   24.22  551.53   27.25   551.5   48.44   551.7
   54.49  551.65   60.32  551.24   63.12  551.16   65.93  550.97   71.53  550.22
   74.34   549.8   77.14   549.5   79.94  549.76   88.47   551.6   91.39  551.98
    94.3   552.2   97.22  552.87  100.14  553.97  117.64  562.68  120.56  563.67
  123.48  564.15   126.4  565.73  129.32  567.42
#Mann= 3 , 0 , 0
       0      .1       0   71.53     .05       0   79.94      .1       0
Bank Sta=71.53,79.94
XS Rating Curve= 0 ,0
Exp/Cntr=0.3,0.1

Type RM Length L Ch R = 1 ,1097.28 ,86.47,91.44,94.81
XS GIS Cut Line= 6
     610112.3489    4326515.0864     610103.1593    4326467.9667
     610101.8974    4326452.3907     610099.0363    4326444.7746
     610102.0128     4326429.561     610092.4693    4326381.1203
#Sta/Elev= 21
       0  567.94       9   560.4      18  553.21      21  550.98      24  549.89
      27  549.89   48.01  548.67   53.22  548.24   55.82  548.03   58.43  548.01
   61.03  547.79   63.63  547.92   66.35  548.28   71.77  548.94   84.69  549.87
   90.18  550.05   107.6  551.59  110.51     552  113.41  553.07  119.22  554.89
  136.64  566.87
#Mann= 3 , 0 , 0
       0      .1       0   53.22     .05       0   66.35      .1       0
Bank Sta=53.22,66.35
XS Rating Curve= 0 ,0
Exp/Cntr=0.3,0.1

Type RM Length L Ch R = 1 ,1005.84 ,95.18,91.44,79.92
XS GIS Cut Line= 6
     610182.6198     4326510.929     610184.6291    4326470.2408
     610186.5522    4326448.3846     610189.3521     4326434.945
     610191.9317    4326427.2075     610200.2056    4326351.3127
#Sta/Elev= 30
       0  566.21    2.91  565.53    5.82  563.96   11.64  559.34   20.37  552.74
   23.28  550.77   26.19  549.58    29.1  549.29   34.92   549.1   51.71  547.83
   65.42  547.23   72.57  546.83   76.41  546.99   79.13  547.28   90.67   548.3
   99.83  548.44  108.99  548.31  112.05  548.38  118.15  548.89  121.21  549.47
  124.26   549.6  127.32   550.5  130.37  551.91  133.42  553.67  142.58     560
  145.64  561.98  151.75  565.38   154.8  565.88  157.85  566.83  160.91  568.29
#Mann= 3 , 0 , 0
       0      .1       0   65.42     .05       0   79.13      .1       0
Bank Sta=65.42,79.13
XS Rating Curve= 0 ,0
Exp/Cntr=0.3,0.1

Type RM Length L Ch R = 1 ,914.4   ,31.6,91.44,62.02
XS GIS Cut Line= 4
     610270.3717    4326508.7329     610277.6561    4326433.2961
       610267.25    4326405.8727     610251.7995    4326357.6627
#Sta/Elev= 26
       0  558.35    6.06  555.08    9.09   554.1   12.13   553.5   18.19  550.21
   21.22  548.77   24.25  548.12   36.38  547.09   39.41  546.93   42.44   546.9
   66.69  545.58   69.72  545.44   75.79  545.39   81.65  545.56   90.45  545.27
   93.39  545.51   99.25  546.58  102.19  546.64  111.08  547.94  120.01  549.77
  128.94  551.01  131.92  551.72   134.9  551.97  143.83  554.85  152.77  557.46
  155.74  558.46
#Mann= 3 , 0 , 0
       0      .1       0   66.69     .05       0   93.39      .1       0
Bank Sta=66.69,93.39
XS Rating Curve= 0 ,0
Exp/Cntr=0.3,0.1

Type RM Length L Ch R = 1 ,822.96  ,90.57,91.44,59.36
XS GIS Cut Line= 6
     610302.5996     4326516.413     610308.8295    4326437.6816
     610312.8971    4326421.8118     610316.2718    4326420.7905
     610322.7156    4326423.2267     610339.9059    4326334.6439
#Sta/Elev= 30
       0  558.76   18.23  549.78    24.3  548.32   27.34  547.79   36.45  547.42
    48.6  546.72   57.71   546.5   66.83  546.47    72.9  546.07   78.98  545.25
   81.71  544.99   87.17  544.89   92.63  545.25     107  544.96  110.01  545.15
  122.04  545.45  128.05  545.82  131.06  545.82  143.09  546.79   146.1   547.2
  149.11  547.99  152.12  549.07  158.13  551.59  164.15  552.58  167.16  553.37
  173.17  554.58  188.21  557.24  191.22  557.68  194.23  557.71  197.24  558.28
#Mann= 3 , 0 , 0
       0      .1       0   78.98     .05       0  110.01      .1       0
Bank Sta=78.98,110.01
XS Rating Curve= 0 ,0
Exp/Cntr=0.3,0.1

Type RM Length L Ch R = 1 ,731.52  ,79.71,91.44,88.71
XS GIS Cut Line= 5
     610391.4997     4326532.288     610394.9052    4326427.9074
     610388.2867    4326412.1886      610372.168    4326384.4842
      610368.481    4326333.8501
#Sta/Elev= 26
       0  558.13   15.36  550.76   18.43  550.43    21.5  549.23   24.57  547.73
   27.64  546.74   30.72  546.42   46.07  545.82   58.36  545.53   82.93  545.12
  104.44  544.45  118.65   544.2  127.32   543.9  130.23  543.94  133.15  544.17
  138.97  544.91   144.8   545.2  153.54  546.16  159.52  546.99   162.5  547.74
  168.48  549.48  171.46  549.76  174.45  550.36  198.34  557.45  201.33  557.97
  204.31  558.32
#Mann= 3 , 0 , 0
       0      .1       0  118.65     .05       0  133.15      .1       0
Bank Sta=118.65,133.15
XS Rating Curve= 0 ,0
Exp/Cntr=0.3,0.1

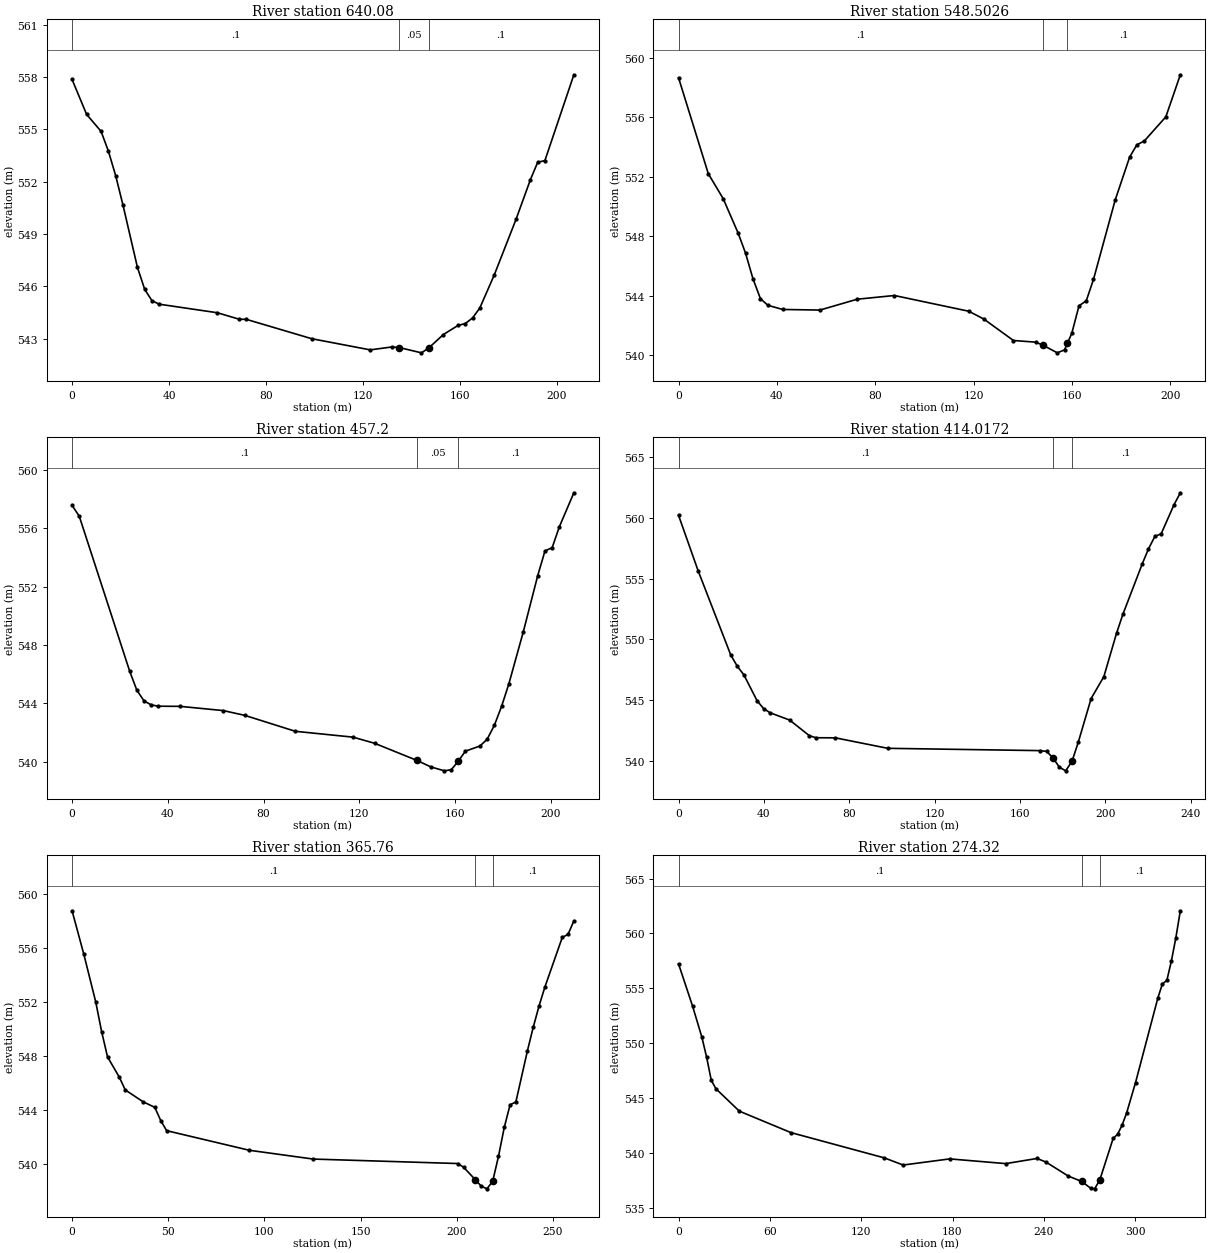
Type RM Length L Ch R = 1 ,640.08  ,85.31,91.58,96.32
XS GIS Cut Line= 5
     610458.9686     4326544.988     610467.6818    4326443.5247
     610449.7539    4326398.7051      610442.398     4326385.574
     610436.4449    4326344.2328
#Sta/Elev= 30
       0  557.86    5.99  555.86   11.98  554.88   14.98  553.75   17.97  552.35
   20.97  550.67   26.96  547.08   29.95  545.82   32.95  545.17   35.94  544.97
    59.9  544.48   68.89  544.11   71.88   544.1   98.84  542.99  122.96  542.35
  132.01  542.52  135.02  542.48  144.07  542.18  147.09  542.46  153.12  543.23
  159.14  543.75  162.15  543.86  165.16  544.18  168.14  544.75  174.11  546.65
  183.06  549.83  189.03  552.12  192.01  553.11  194.99  553.21  206.93  558.13
#Mann= 3 , 0 , 0
       0      .1       0  135.02     .05       0  147.09      .1       0
Bank Sta=135.02,147.09
XS Rating Curve= 0 ,0
Exp/Cntr=0.3,0.1

Type RM Length L Ch R = 1 ,548.5026,87.19,91.3,93.15
XS GIS Cut Line= 3
     610534.6396    4326571.8433      610539.509       4326429.7
     610536.7563    4326367.9814
#Sta/Elev= 30
       0  558.67    12.1  552.21   18.16  550.53   24.21  548.22   27.23  546.87
   30.26  545.14   33.29   543.8   36.31  543.35   42.37  543.07    57.5  543.03
   72.63  543.76   87.76  544.01  118.02  542.95  124.07  542.43  136.17  540.98
  145.17  540.87  148.11  540.67  153.99  540.15  156.94  540.35   158.1   540.8
  159.88  541.46  162.82  543.32  165.76  543.65   168.7  545.09  177.53  550.44
  183.41  553.33  186.36  554.16   189.3   554.4  198.12  556.04  204.01  558.87
#Mann= 3 , 0 , 0
       0      .1       0  148.11     .05       0   158.1      .1       0
Bank Sta=148.11,158.1
XS Rating Curve= 0 ,0
Exp/Cntr=0.3,0.1

Type RM Length L Ch R = 1 ,457.2   ,50.44,43.18,41.35
XS GIS Cut Line= 4
     610573.0043    4326582.4267     610625.6575     4326454.411
     610628.1718    4326431.6423     610637.8285    4326384.2963
#Sta/Elev= 30
       0  557.58    3.01  556.83   24.07  546.21   27.08   544.9   30.09  544.17
    33.1   543.9   36.11  543.81   45.14   543.8   63.19  543.51   72.22  543.18
   93.28  542.09  117.36  541.69  126.38  541.27  144.15  540.09  149.87  539.65
   155.6  539.38  158.46  539.46  161.33  540.04  164.35  540.73  170.39  541.08
  173.41  541.54  176.43   542.5  179.45   543.8  182.47  545.33  188.51   548.9
  194.55  552.76  197.57  554.45  200.59  554.68  203.61  556.12  209.65  558.44
#Mann= 3 , 0 , 0
       0      .1       0  144.15     .05       0  161.33      .1       0
Bank Sta=144.15,161.33
XS Rating Curve= 0 ,0
Exp/Cntr=0.3,0.1

Type RM Length L Ch R = 1 ,414.0172,56.02,48.26,48.18
XS GIS Cut Line= 4
     610610.6653    4326601.2685     610668.2123    4326486.1745
      610673.504    4326451.7786     610662.2592    4326381.0024
#Sta/Elev= 30
       0   560.2    9.19  555.64   24.51  548.71   27.57  547.79   30.64  547.09
   36.77  544.98   39.83  544.33   42.89  543.98   52.08  543.38   61.28   542.1
   64.34  541.93   73.53  541.92   98.04  541.06  169.45  540.87  172.44  540.81
  175.42  540.29  178.41  539.52   181.4  539.21  184.38  539.99  187.37  541.59
  193.34  545.15  199.31  546.95  205.28  550.53  208.27  552.09  217.23  556.18
  220.21  557.44   223.2  558.46  226.19  558.69  232.16  561.06  235.14  562.05
#Mann= 3 , 0 , 0
       0      .1       0  175.42     .05       0  184.38      .1       0
Bank Sta=175.42,184.38
XS Rating Curve= 0 ,0
Exp/Cntr=0.3,0.1

Type RM Length L Ch R = 1 ,365.76  ,79.08,91.44,94.32
XS GIS Cut Line= 4
     610655.0253    4326616.8226     610720.8417    4326539.7393
     610726.0063    4326473.9218     610710.9722    4326381.7117
#Sta/Elev= 30
       0  558.74    6.14  555.51   12.29  552.01   15.36  549.81   18.43  547.94
   24.57  546.44   27.64   545.5   36.86  544.63      43  544.21   46.07  543.24
   49.14  542.49   92.14  541.04  125.37  540.39  200.53  540.06  203.54  539.78
  209.57  538.87  212.59   538.4   215.6  538.19  218.61  538.74  221.63  540.59
  224.64  542.73  227.65   544.4  230.67  544.61   236.7  548.41  239.71  550.14
  242.72  551.71  245.74   553.1  254.78  556.77  257.79     557  260.81  557.99
#Mann= 3 , 0 , 0
       0      .1       0  209.57     .05       0  218.61      .1       0
Bank Sta=209.57,218.61
XS Rating Curve= 0 ,0
Exp/Cntr=0.3,0.1

Type RM Length L Ch R = 1 ,274.32  ,105.35,274.32,233.92
XS GIS Cut Line= 5
     610686.7753     4326641.958     610796.5788    4326543.3774
     610806.1278    4326476.6622     610809.4831    4326412.0767
     610816.1051    4326362.4814
#Sta/Elev= 30
       0  557.22    9.22  553.37   15.37  550.52   18.45  548.71   21.52   546.6
   24.59  545.83   39.97  543.79   73.78  541.84  135.27  539.53  147.56  538.88
   178.2  539.44  214.96  539.01  235.54  539.48  241.42  539.15  256.11  537.87
  264.93  537.38  270.81  536.76  273.31  536.71  276.69  537.49  285.52   541.3
  288.46  541.69   291.4  542.51  294.35  543.61  300.23  546.39  314.95  554.13
  317.89  555.39  320.84  555.72  323.78  557.47  326.72  559.59  329.67  562.06
#Mann= 3 , 0 , 0
       0      .1       0  264.93     .05       0  276.69      .1       0
Bank Sta=264.93,276.69
XS Rating Curve= 0 ,0
Exp/Cntr=0.3,0.1
LCMann Table=0

Chan Stop Cuts=-1
Use User Specified Reach Order=0
Composite Channel Slope=5